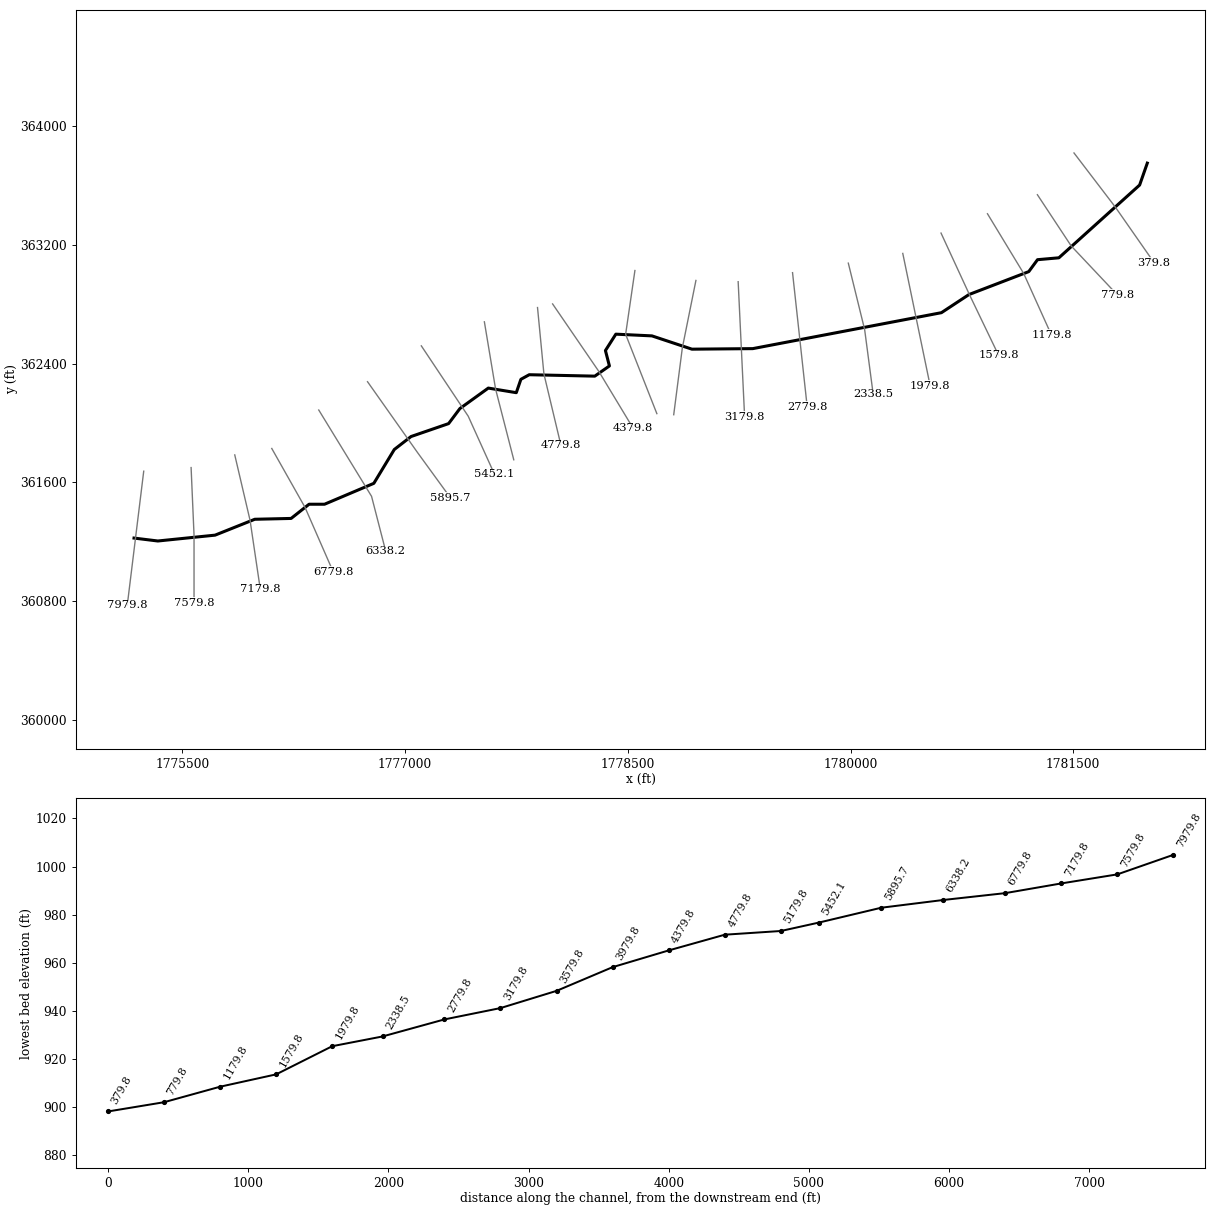
--- IcsRn.prj (project) ---

Proj Title=IcsRn
Current Plan=p01
Default Exp/Contr=0,0
English Units
Geom File=g01
Flow File=f01
Plan File=p01
BEGIN DESCRIPTION:
END DESCRIPTION:
DSS Export Rating Curves= 0
DSS Export Rating Curve Sorted= 0
DSS Export Volume Flow Curves= 0
DXF OffsetX= 0
DXF OffsetY= 0
DXF ScaleX= 0
DXF ScaleY= 0

--- IcsRn.p01 (plan) ---

Plan Title=Floodplain
Program Version=4.00
Geom File=g01
Flow File=f01
K Sum by GR=0
Std Step Tol=0.01
Critical Tol=0.01
Num of Std Step Trials=20
Max Error Tol=0.3
Flow Tol Ratio=0.001
Split Flow NTrial=30
Split Flow Tol=0.02
Split Flow Ratio=0.02
Log Output Level=0
Friction Slope Method=1
Unsteady Friction Slope Method=2
Unsteady Bridges Friction Slope Method=1
Global Log Level=0
CheckData=False
Run HTab=0
Run UNet=0
Run PostProcess=0
UNET Theta=0
UNET Theta Warmup=0
UNET ZTol=0
UNET ZSATol=0
UNET MxIter=0
UNET MaxInSteps=0
UNET DtIC=0
UNET DtMin=0
UNET MaxCRTS=0
UNET WFStab=0
UNET SFStab=0
UNET WFX=0
UNET SFX=0
UNET DSS MLevel=0
UNET DZMax Abort=0
UNET Convert EG Bridges=0
UNET Use Existing IB Tables=0
UNET Froude Limit=0
UNET Froude Power=0
Write IC File=0
Echo Input=False
Echo Output=False
Write Detailed=0

--- IcsRn.f01 (steady flow) ---

Flow Title=NFF Regression Equation
Program Version=4.00
Number of Profiles=1
Profile Names=P100yr
River Rch & RM=IcsRn,Main      ,7979.8
768.1730
River Rch & RM=IcsRn,Main      ,5452.1
843.7612
River Rch & RM=IcsRn,Main      ,2779.8
925.8749
River Rch & RM=IcsRn,Main      ,379.8
1027.066
Boundary for River Rch & Prof#=IcsRn,Main      ,1
Up Type=0
Dn Type=3
Dn Slope=0.015274

--- IcsRn.g01 (geometry) ---

Geom Title=USGS 3m DEM
Program Version=4.00

River Reach=IcsRn           ,Main
Reach XY= 30
     1775174.832       361224.71     1775335.204      361205.015
      1775720.66      361244.404     1775987.948      361351.319
     1776232.726      361356.946     1776353.709      361452.607
      1776457.81      361452.607     1776789.808      361593.284
     1776927.672      361821.182     1777040.214      361908.402
     1777293.433      361995.621     1777369.399      362096.909
     1777560.721      362234.773     1777749.228      362203.824
     1777780.177      362293.857     1777836.448      362324.807
     1778277.941      362315.202     1778376.388      362383.951
     1778349.537      362487.651     1778419.625      362597.891
     1778662.664      362586.361     1778932.086      362496.844
      1779341.77      362500.501     1780612.322      362742.625
      1780797.78      362864.717     1781200.434      363019.154
     1781259.406      363099.441     1781403.271      363112.179
     1781947.048      363602.217     1781998.767      363749.767

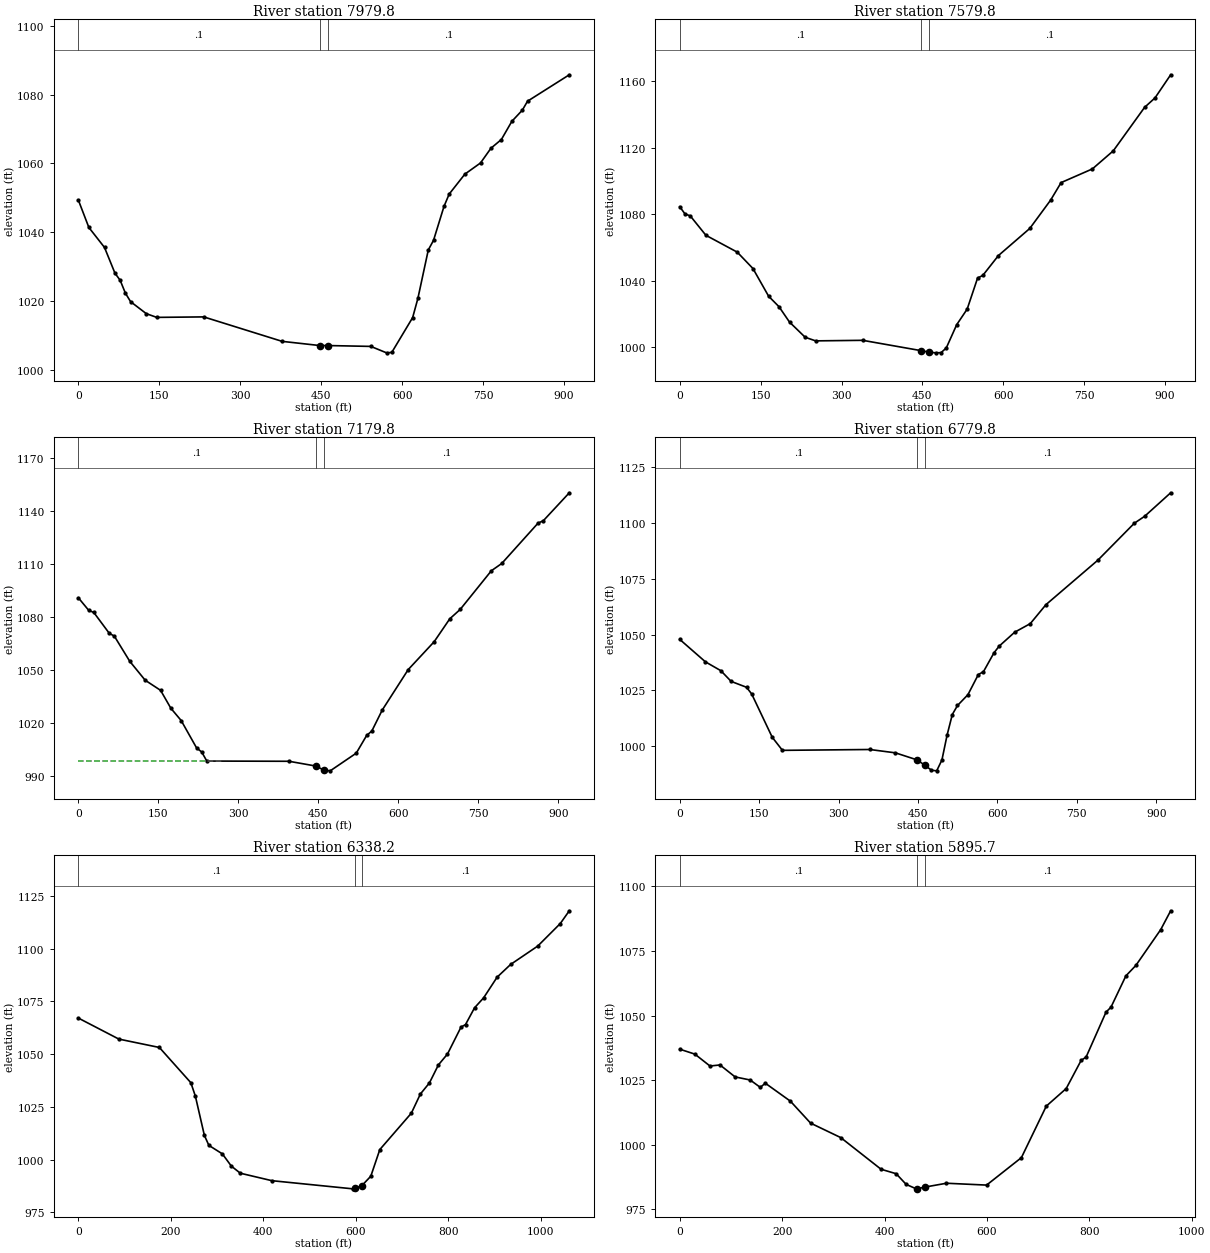
Type RM Length L Ch R = 1 ,7979.8  ,396.212,400,402.811
XS GIS Cut Line= 3
     1775240.219      361675.098     1775184.758      361223.491
     1775129.297      360771.883
#Sta/Elev= 30
       0 1049.27    19.4 1041.34    48.4 1035.53    67.8 1028.04    77.4 1025.99
    87.1 1022.25    96.8 1019.76   125.9 1016.28   145.2  1015.2   232.3 1015.34
   377.6 1008.23   447.5 1007.01   462.5 1007.01   542.1 1006.76   571.2 1004.89
   580.9 1005.01   619.6 1015.14   629.3 1020.71   648.6 1034.81   658.3  1037.6
   677.7 1047.46   687.3 1051.05   716.4 1056.85   745.4  1060.1   764.8 1064.39
   784.1 1066.92   803.5  1072.2   822.9 1075.45   832.6 1078.06     910 1085.74
#Mann= 3 , 0 , 0
       0      .1       0   447.5    .045       0   462.5      .1       0
Bank Sta=447.5,462.5
XS Rating Curve= 0 ,0
Exp/Cntr=0.3,0.1

Type RM Length L Ch R = 1 ,7579.8  ,395.588,400,403.525
XS GIS Cut Line= 3
     1775559.245      361699.496     1775579.018      361244.404
     1775579.018      360789.496
#Sta/Elev= 30
       0 1084.61     9.7 1080.29    19.4 1079.15    48.5 1067.45   106.6 1057.32
   135.7 1047.47   164.8  1030.8   184.1 1024.47   203.5 1015.26   232.6 1006.11
     252 1003.95   339.2 1004.28     448  998.04     463  997.12   474.9  996.75
   484.6  996.88   494.2  999.65   513.6 1013.69     533 1023.06   552.3 1041.73
     562 1043.33     591 1055.28   649.1 1071.57   687.8 1088.63   707.2 1099.15
   765.2 1107.38     804 1118.27     862  1144.4   881.4 1150.12   910.4 1164.01
#Mann= 3 , 0 , 0
       0      .1       0     448    .045       0     463      .1       0
Bank Sta=448,463
XS Rating Curve= 0 ,0
Exp/Cntr=0.3,0.1

Type RM Length L Ch R = 1 ,7179.8  ,393.442,400,406.032
XS GIS Cut Line= 3
     1775853.224      361784.769     1775956.398      361343.935
     1776025.017      360881.225
#Sta/Elev= 30
       0 1090.74    19.3  1083.7    28.9 1082.46    57.8 1070.73    67.4 1069.09
    96.3 1054.88   125.2 1044.19   154.1 1038.47   173.4 1028.33   192.7 1021.41
   221.6 1005.94   231.2 1003.63   240.8  998.51   394.9  998.38   445.2  995.69
   460.2  993.43   472.2  992.98     521 1002.97   540.5 1012.97   550.2 1015.48
   569.7 1027.31   618.4 1050.18   667.1 1065.95   696.4  1078.9   715.9 1084.19
   774.3 1106.03   793.8 1110.15     862 1132.99   871.8 1134.32   920.5 1150.11
#Mann= 3 , 0 , 0
       0      .1       0   445.2    .045       0   460.2      .1       0
#XS Ineff= 2 , 0
          269.75   998.8
Permanent Ineff=
       F       F
Bank Sta=445.2,460.2
XS Rating Curve= 0 ,0
Exp/Cntr=0.3,0.1

Type RM Length L Ch R = 1 ,6779.8  ,441.077,441.597,444.507
XS GIS Cut Line= 3
     1776102.564      361828.083     1776326.588      361431.163
     1776515.391      360999.279
#Sta/Elev= 30
       0 1047.81    48.5 1037.76    77.6  1033.8      97 1029.01   126.1 1026.37
   135.8 1023.38   174.6 1003.99   193.9  998.12   358.8   998.5   407.3     997
   448.3  993.84   463.3  991.36   475.4  989.21   485.2  988.94   495.1   993.8
   504.9    1005   514.7 1014.17   524.5 1018.21   544.2 1023.05   563.8 1032.05
   573.6 1033.38   593.3 1041.76   603.1 1044.78   632.5 1051.04     662 1054.89
   691.5 1063.37   789.6 1083.31   858.4 1099.85     878 1102.98   927.1  1113.5
#Mann= 3 , 0 , 0
       0      .1       0   448.3    .045       0   463.3      .1       0
Bank Sta=448.3,463.3
XS Rating Curve= 0 ,0
Exp/Cntr=0.3,0.1

Type RM Length L Ch R = 1 ,6338.2  ,440.406,442.469,444.533
XS GIS Cut Line= 3
     1776418.924      362087.103      1776774.49      361505.853
     1776869.624      361137.065
#Sta/Elev= 30
       0 1067.07    87.6 1057.11   175.2 1053.14   243.3 1036.43   253.1 1030.05
   272.6 1011.44   282.3 1006.71   311.5 1002.67     331  996.85   350.4   993.5
   418.6  989.96   593.8  986.09   598.1   986.3   613.1  987.55   632.7  992.08
   652.2 1004.72   720.4 1021.97     740 1031.08   759.5 1036.31     779 1044.88
   798.6 1050.03   827.9 1062.81   837.6    1064   857.2 1071.96   876.7 1076.65
     906 1086.48   935.3 1092.53   993.9 1101.23  1042.7 1111.92  1062.2 1117.97
#Mann= 3 , 0 , 0
       0      .1       0   598.1    .045       0   613.1      .1       0
Bank Sta=598.1,613.1
XS Rating Curve= 0 ,0
Exp/Cntr=0.3,0.1

Type RM Length L Ch R = 1 ,5895.7  ,444.46,443.575,442.689
XS GIS Cut Line= 3
     1776747.378      362277.655     1777081.818      361803.865
     1777304.778      361497.295
#Sta/Elev= 30
       0 1036.97    29.5 1035.06      59 1030.45    78.6 1030.86   108.1 1026.23
   137.6 1025.03   157.3 1022.18   167.1 1023.79   216.2 1016.82   255.6 1008.32
   314.5 1002.72   393.2  990.46   422.7  988.73   442.3  984.59     462  982.87
   464.2   982.9   479.2  983.56     521  985.04   599.4  984.32   667.4  994.96
     716 1014.91   754.9 1021.72   784.1 1032.63   793.8 1033.93   832.7 1051.33
   842.4 1053.25   871.5 1065.37     891 1069.42   939.6 1083.31     959 1090.59
#Mann= 3 , 0 , 0
       0      .1       0   464.2    .045       0   479.2      .1       0
Bank Sta=464.2,479.2
XS Rating Curve= 0 ,0
Exp/Cntr=0.3,0.1

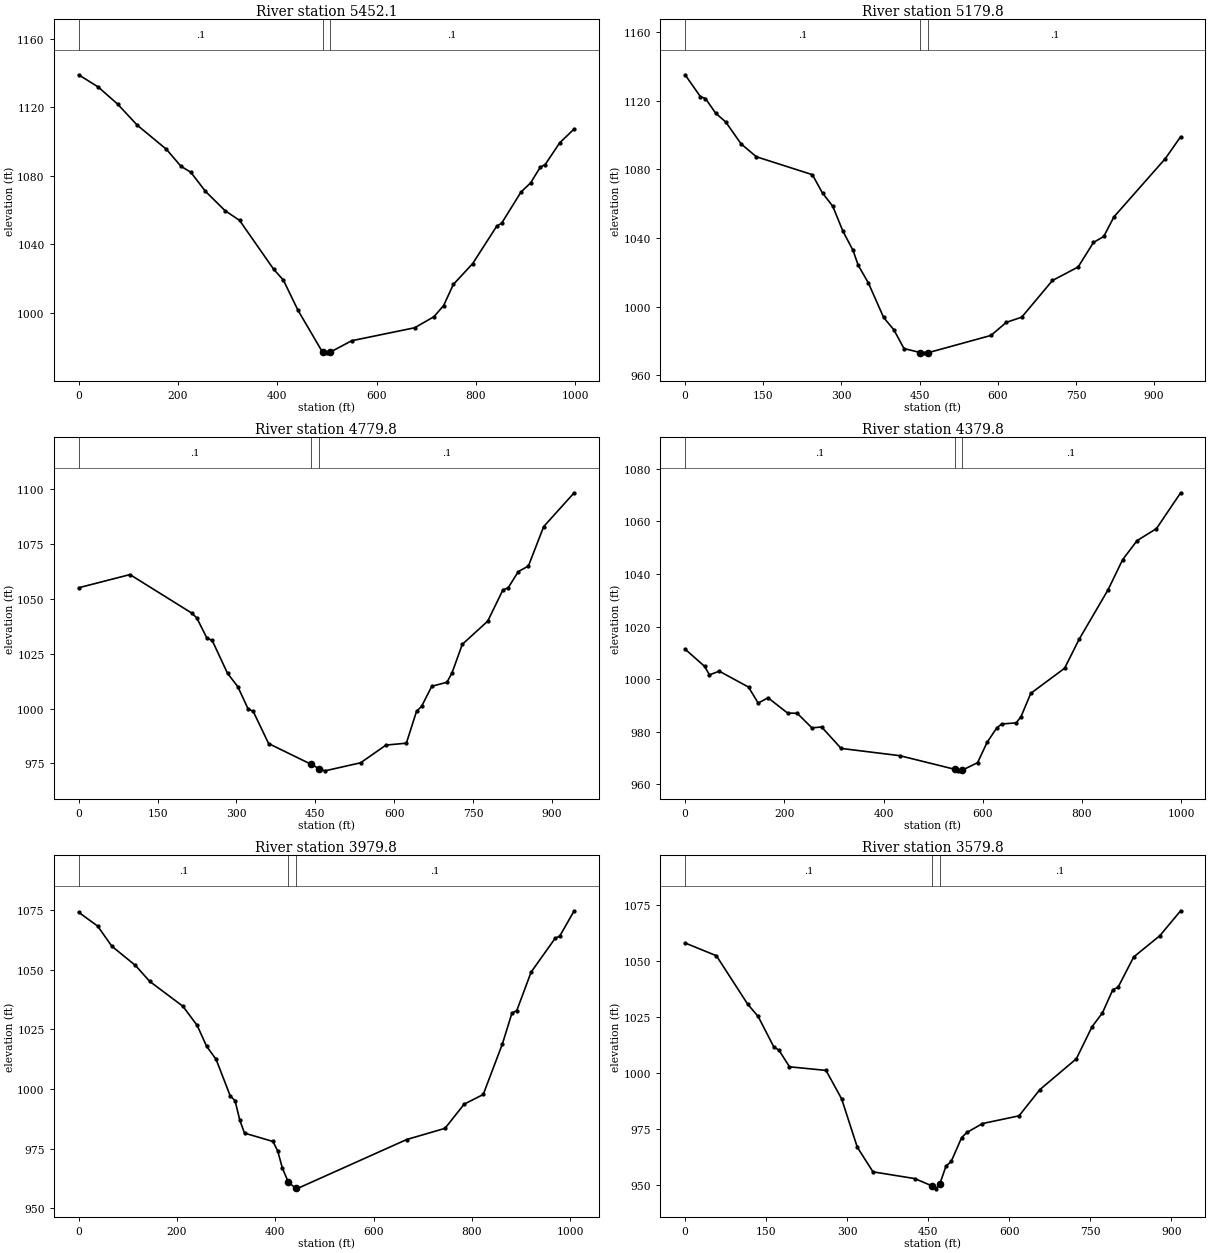
Type RM Length L Ch R = 1 ,5452.1  ,282.878,272.359,264.03
XS GIS Cut Line= 3
     1777109.688      362519.196     1777425.548      362045.405
     1777602.059      361655.225
#Sta/Elev= 30
       0 1139.03    39.3 1131.92    78.5 1121.93   117.8 1109.66   176.7 1095.54
   206.2 1085.58   225.8 1082.16   255.3 1071.01   294.5 1059.78     324 1054.04
   392.7 1025.49   412.3 1019.13   441.8 1001.47     491  977.12   500.7  976.71
     506  977.03   549.8  983.78   676.5  991.34   715.4   997.8   734.9 1004.32
   754.4 1016.64   793.3 1028.78   841.9 1050.71   851.7 1052.39   890.6 1070.56
   910.1 1075.95   929.5 1085.12   939.3 1086.63   968.5 1099.27   997.7 1107.41
#Mann= 3 , 0 , 0
       0      .1       0     491    .045       0     506      .1       0
Bank Sta=491,506
XS Rating Curve= 0 ,0
Exp/Cntr=0.3,0.1

Type RM Length L Ch R = 1 ,5179.8  ,395.854,400,401.512
XS GIS Cut Line= 3
     1777534.266      362681.042     1777609.778      362228.232
     1777732.185      361752.017
#Sta/Elev= 30
       0 1135.06    29.3 1122.37    39.1 1121.23    58.6 1112.72    78.1 1107.55
   107.4 1094.84   136.7 1087.34   244.2  1076.9   263.7 1066.17   283.3 1058.56
   302.8 1044.02   322.3  1032.8   332.1 1024.19   351.6 1013.92   380.9  993.77
   400.5  986.64     420  975.68   451.6  973.34   459.1  973.19   466.6  973.29
   586.9  983.33   616.4  990.95   645.9  993.95   704.9 1015.32   754.1 1023.17
   783.6 1037.46   803.3 1040.93   822.9 1052.37   921.3 1086.23   950.8 1098.99
#Mann= 3 , 0 , 0
       0      .1       0   451.6    .045       0   466.6      .1       0
Bank Sta=451.6,466.6
XS Rating Curve= 0 ,0
Exp/Cntr=0.3,0.1

Type RM Length L Ch R = 1 ,4779.8  ,376.804,400,408.484
XS GIS Cut Line= 3
     1777892.188      362777.144     1777935.241      362330.223
     1778049.584      361850.657
#Sta/Elev= 30
       0 1054.95    97.6 1060.95   214.7 1043.48   224.5 1041.26     244 1031.99
   253.8 1031.03   283.1 1015.99   302.6 1009.95   322.1  999.85   331.9   998.7
   361.1  984.07   441.5  974.68   456.5   972.7   468.3  971.65     536  975.31
   584.3  983.37     623  984.23   642.3  998.74     652 1001.01   671.3 1010.12
   700.3 1011.97     710 1016.35   729.3  1029.2   777.7 1039.78   806.7 1054.07
   816.3 1054.83   835.7 1062.28     855 1064.85     884 1082.77     942 1098.17
#Mann= 3 , 0 , 0
       0      .1       0   441.5    .045       0   456.5      .1       0
Bank Sta=441.5,456.5
XS Rating Curve= 0 ,0
Exp/Cntr=0.3,0.1

Type RM Length L Ch R = 1 ,4379.8  ,416.801,400,397.506
XS GIS Cut Line= 3
     1777993.784      362801.488     1778304.852      362347.346
     1778536.539      361963.477
#Sta/Elev= 30
       0 1011.42    39.3 1004.88    49.1 1001.63    68.8 1003.04   127.8  996.99
   147.4  990.89   167.1  992.92   206.4  987.12   226.1     987   255.6  981.46
   275.2   981.8   314.5  973.64   432.5  970.89     543  965.72   550.5  965.11
     558  965.29   589.5  968.22   608.9  976.02   628.4  981.51   638.2  982.95
   667.4  983.36   677.2  985.78   696.7  994.59   764.9 1004.15   794.1 1015.14
   852.6 1034.04   881.9 1045.48   911.1 1052.74   950.1  1057.3   998.8 1070.93
#Mann= 3 , 0 , 0
       0      .1       0     543    .045       0     558      .1       0
Bank Sta=543,558
XS Rating Curve= 0 ,0
Exp/Cntr=0.3,0.1

Type RM Length L Ch R = 1 ,3979.8  ,401.328,400,387.394
XS GIS Cut Line= 3
     1778548.104      363026.484     1778485.553      362597.049
     1778695.825      362062.747
#Sta/Elev= 30
       0 1073.99    38.6 1068.23    67.5 1059.79   115.7  1051.7   144.7 1045.03
   212.2 1034.62   241.1 1026.62   260.4 1017.86   279.7 1012.38   308.6  996.98
   318.2  995.12   327.9  986.89   337.5  981.49   395.4  977.99     405     974
   414.7  966.72   426.5  961.06   441.5  958.36   443.7  958.15   667.5  978.81
   745.4  983.49   784.3  993.61   823.2  997.67   862.2 1018.88   881.6 1031.77
   891.4 1032.81   920.6 1048.94   969.2 1063.01     979 1064.06  1008.2 1074.62
#Mann= 3 , 0 , 0
       0      .1       0   426.5    .045       0   441.5      .1       0
Bank Sta=426.5,441.5
XS Rating Curve= 0 ,0
Exp/Cntr=0.3,0.1

Type RM Length L Ch R = 1 ,3579.8  ,394.433,400,403.975
XS GIS Cut Line= 3
      1778958.94      362959.646     1778867.378      362505.184
     1778809.413       362055.42
#Sta/Elev= 30
       0 1057.87    57.9 1052.18   115.9 1030.57   135.2 1025.11   164.2 1011.54
   173.8 1010.06   193.2 1002.68   260.8 1001.07   289.7  988.39   318.7  966.82
   347.7  955.86     425  952.85   456.1  949.69   463.6  948.28   471.1  950.28
   482.9  958.43   492.5  960.48   511.8  971.12   521.5  973.41   550.4  977.38
     618  980.82   656.6  992.52   724.1 1006.25   753.1 1020.53   772.3 1026.69
   791.6 1037.02   801.3 1038.12   830.2 1051.63   878.5 1061.09   917.1 1072.22
#Mann= 3 , 0 , 0
       0      .1       0   456.1    .045       0   471.1      .1       0
Bank Sta=456.1,471.1
XS Rating Curve= 0 ,0
Exp/Cntr=0.3,0.1

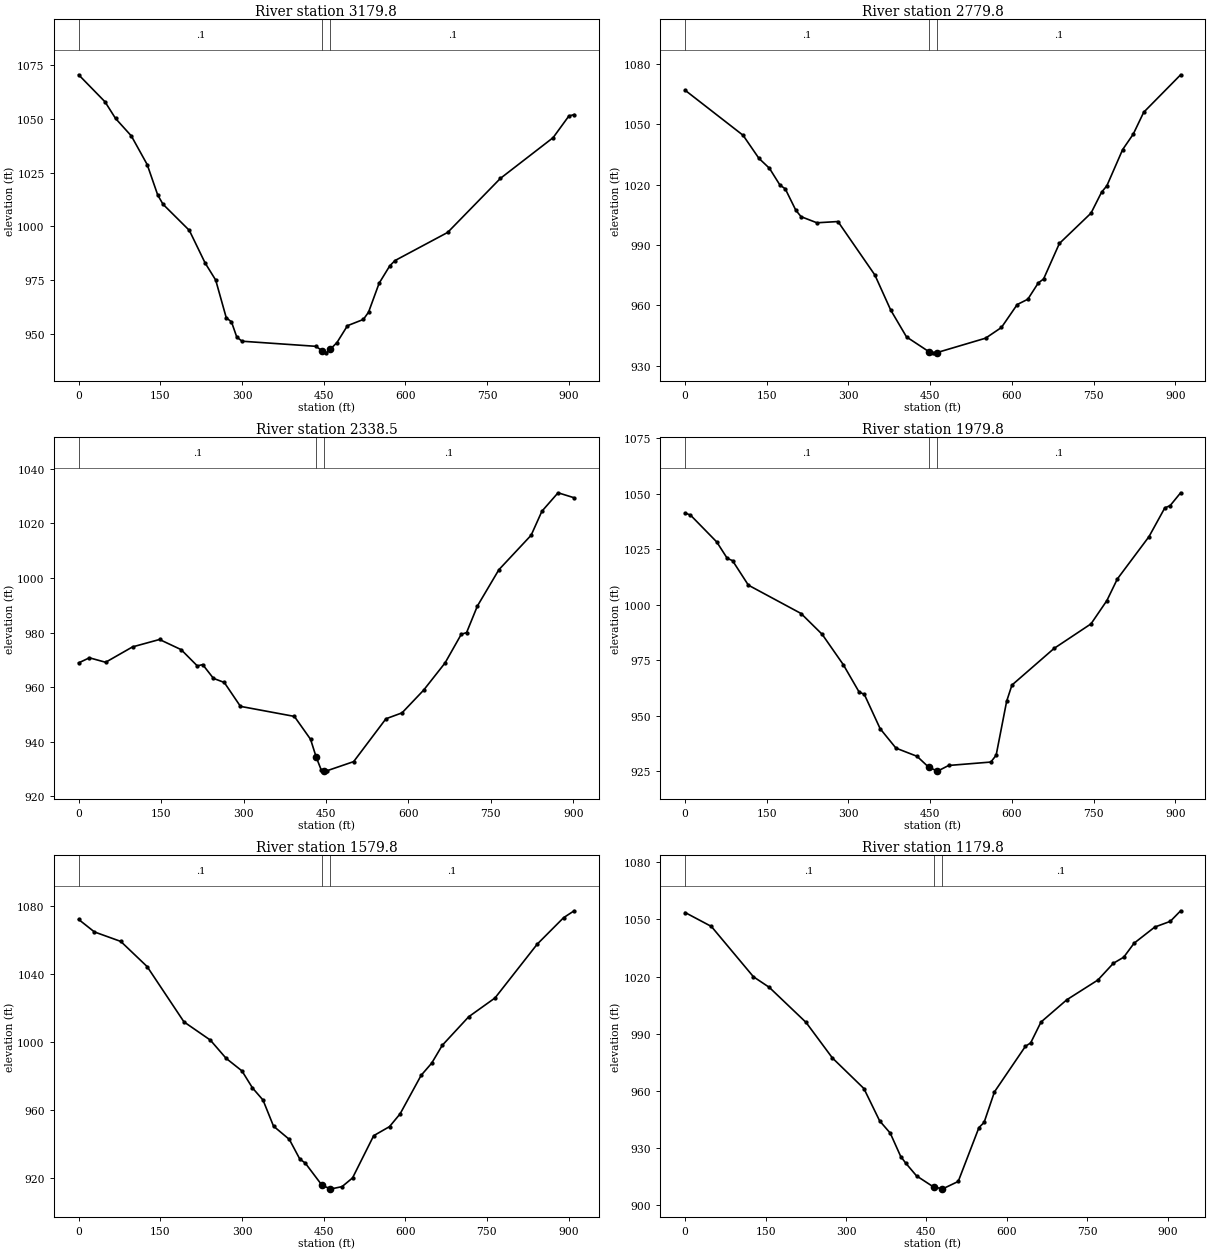
Type RM Length L Ch R = 1 ,3179.8  ,398.622,400,401.378
XS GIS Cut Line= 3
     1779243.408      362951.325     1779265.096      362496.842
     1779286.784      362042.359
#Sta/Elev= 30
       0 1070.57    48.4    1058    67.8 1050.23    96.8 1042.09   125.9 1028.77
   145.2 1014.62   154.9 1010.31   203.3  998.12   232.3  982.94   251.7     975
   271.1  957.45   280.7  955.53   290.4  948.47   300.1  946.53   435.6  944.16
   447.5  942.03     455  941.12   462.5  942.87   474.4  945.91   493.7  953.76
   522.8  956.66   532.4  960.05   551.8  973.52   571.2  981.55   580.9  984.07
   677.7  997.18   774.5 1022.33   871.3 1041.29   900.3 1051.39     910 1052.03
#Mann= 3 , 0 , 0
       0      .1       0   447.5    .045       0   462.5      .1       0
Bank Sta=447.5,462.5
XS Rating Curve= 0 ,0
Exp/Cntr=0.3,0.1

Type RM Length L Ch R = 1 ,2779.8  ,438.305,441.289,444.169
XS GIS Cut Line= 3
     1779609.621      363012.199     1779659.024      362559.889
     1779708.428      362107.579
#Sta/Elev= 30
       0 1067.04   106.5 1044.62   135.5 1033.18   154.9 1028.21   174.3 1019.81
   183.9 1018.01   203.3 1007.36     213 1004.14     242  1001.1   280.7 1001.72
   348.5  975.12   377.6  957.68   406.6  944.32   447.5  937.02     455   936.4
   462.5  936.52   551.8  943.69   580.9  949.01   609.9  960.43   629.3  963.05
   648.6  971.18   658.3  973.14   687.3   990.8   745.4 1005.89   764.8 1016.31
   774.5  1019.5   803.5 1037.52   822.9 1045.17   842.2 1056.09     910 1074.73
#Mann= 3 , 0 , 0
       0      .1       0   447.5    .045       0   462.5      .1       0
Bank Sta=447.5,462.5
XS Rating Curve= 0 ,0
Exp/Cntr=0.3,0.1

Type RM Length L Ch R = 1 ,2338.5  ,359.548,358.711,357.978
XS GIS Cut Line= 3
     1779985.185      363076.239     1780095.281       362628.35
     1780152.928      362191.739
#Sta/Elev= 30
       0  968.87    19.6  970.74    49.1   969.1    98.1  974.74   147.2  977.45
   186.5  973.73   215.9  967.77   225.7  968.25   245.3   963.2     265   961.7
   294.4  952.94   392.5  949.26     422  940.86   432.2  934.35   441.6  929.53
   447.2  929.41   451.4  929.31   500.4  932.69   559.1  948.39   588.4  950.56
   627.6  958.86   666.7  968.86   696.1  979.33   705.9     980   725.5  989.71
   764.6 1003.02   823.3 1015.66   842.9 1024.46   872.3 1031.22   901.6 1029.39
#Mann= 3 , 0 , 0
       0      .1       0   432.2    .045       0   447.2      .1       0
Bank Sta=432.2,447.2
XS Rating Curve= 0 ,0
Exp/Cntr=0.3,0.1

Type RM Length L Ch R = 1 ,1979.8  ,394.739,400,405.617
XS GIS Cut Line= 3
     1780352.032      363141.653     1780444.241      362696.095
      1780536.45      362250.536
#Sta/Elev= 30
       0 1041.39     9.7 1040.53    58.1 1028.39    77.4 1020.99    87.1 1019.97
   116.2 1008.92     213  996.14   251.7  986.77   290.4  973.14   319.5  960.79
   329.1  959.72   358.2  944.24   387.2   935.5     426   931.8   447.5  926.85
   462.5  925.28   464.7  925.26     484  927.68   561.5  929.22   571.2   932.3
   590.5  956.62   600.2   963.9   677.7  980.44   745.4  991.48   774.5 1001.95
   793.8 1011.72   851.9 1030.79     881 1043.76   890.6 1044.72     910 1050.54
#Mann= 3 , 0 , 0
       0      .1       0   447.5    .045       0   462.5      .1       0
Bank Sta=447.5,462.5
XS Rating Curve= 0 ,0
Exp/Cntr=0.3,0.1

Type RM Length L Ch R = 1 ,1579.8  ,397.422,400,399.448
XS GIS Cut Line= 3
     1780609.622      363278.691     1780800.167      362865.744
     1780997.525      362455.218
#Sta/Elev= 30
       0 1072.21      29 1064.84    77.4 1059.25   125.8 1044.45   193.5 1011.86
   241.9 1001.15   270.9  990.41     300     983   319.3     973   338.7  965.83
     358  950.46   387.1  942.64   406.4  931.02   416.1   928.8   447.3  915.54
   462.3   913.6   464.5  913.54   483.9  914.84   503.2  919.98     542  944.84
   571.1  950.19   590.5  957.68   629.2   980.4   648.6  987.58     668  998.07
   716.5 1014.87   764.9 1025.96   842.4 1057.64   890.9 1073.24   910.3  1077.3
#Mann= 3 , 0 , 0
       0      .1       0   447.3    .045       0   462.3      .1       0
Bank Sta=447.3,462.3
XS Rating Curve= 0 ,0
Exp/Cntr=0.3,0.1

Type RM Length L Ch R = 1 ,1179.8  ,399.215,400,407.475
XS GIS Cut Line= 3
      1780922.35      363408.833      1781166.39      363006.315
     1781352.787      362593.132
#Sta/Elev= 30
       0 1053.66      49 1046.33   127.5 1019.86   156.9 1014.34   225.6  995.87
   274.6  977.22   333.4  961.13   362.8  944.11   382.5   937.7   402.1  925.38
   411.9  921.75   431.5  915.23   463.2  909.39   478.2  908.51   480.4   908.4
   509.3  912.29   547.9   940.6   557.5   943.3   576.8  959.35   634.7  983.38
   644.3  985.09   663.6  996.07   711.8  1007.8   769.7 1018.17   798.6 1026.98
   817.9 1030.17   837.2 1037.52   875.8 1046.02   904.7 1049.01     924 1054.57
#Mann= 3 , 0 , 0
       0      .1       0   463.2    .045       0   478.2      .1       0
Bank Sta=463.2,478.2
XS Rating Curve= 0 ,0
Exp/Cntr=0.3,0.1

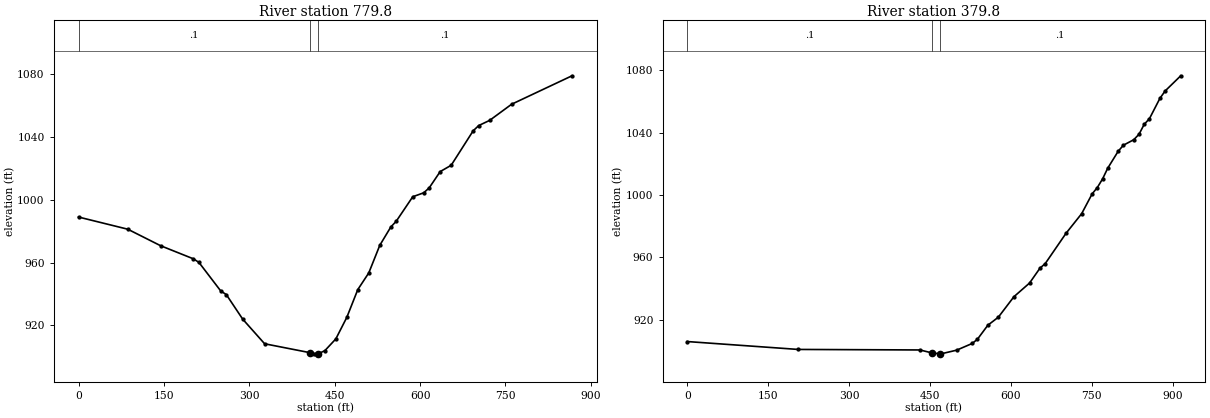
Type RM Length L Ch R = 1 ,779.8   ,398.458,400,396.659
XS GIS Cut Line= 3
     1781258.561      363537.018     1781486.246      363191.995
     1781797.422      362862.034
#Sta/Elev= 30
       0  989.07    86.5  981.32   144.2   970.8   201.9  962.44   211.5  960.18
   249.9  941.95   259.6  939.69   288.4  924.04   326.9  908.36   405.9  902.74
   413.4  901.95   420.9  901.97   432.7  903.98     452  911.47   471.3   925.2
   490.6  942.89   509.9  953.51   529.2  971.06   548.5   982.7   558.1   986.4
   587.1 1001.99   606.4 1004.51     616 1007.65   635.3 1018.01   654.6 1022.03
   693.2 1043.96   702.9 1047.31   722.2 1050.63   760.8 1060.91   866.9 1079.03
#Mann= 3 , 0 , 0
       0      .1       0   405.9    .045       0   420.9      .1       0
Bank Sta=405.9,420.9
XS Rating Curve= 0 ,0
Exp/Cntr=0.3,0.1

Type RM Length L Ch R = 1 ,379.8   ,369.626,379.772,390.884
XS GIS Cut Line= 3
     1781505.066       363818.18      1781784.61      363452.041
     1782044.359      363079.693
#Sta/Elev= 30
       0  905.98   205.8  900.92   431.3  900.59   453.2  898.73   468.2  898.12
   470.3   898.1   499.3  900.45   528.3  904.77   537.9  907.48   557.2  916.46
   576.6  921.59   605.5  934.73   634.5  943.51   653.8  953.05   663.5  955.96
   702.1  975.41   731.1  988.01   750.4 1000.62   760.1 1004.76   769.8 1010.26
   779.4 1017.16   798.7 1027.98   808.4 1031.88   827.7 1035.43   837.4 1038.94
     847 1045.28   856.7 1048.91     876 1061.87   885.7 1066.65   914.7 1076.41
#Mann= 3 , 0 , 0
       0      .1       0   453.2    .045       0   468.2      .1       0
Bank Sta=453.2,468.2
XS Rating Curve= 0 ,0
Exp/Cntr=0.3,0.1

Chan Stop Cuts=-1
Use User Specified Reach Order=0